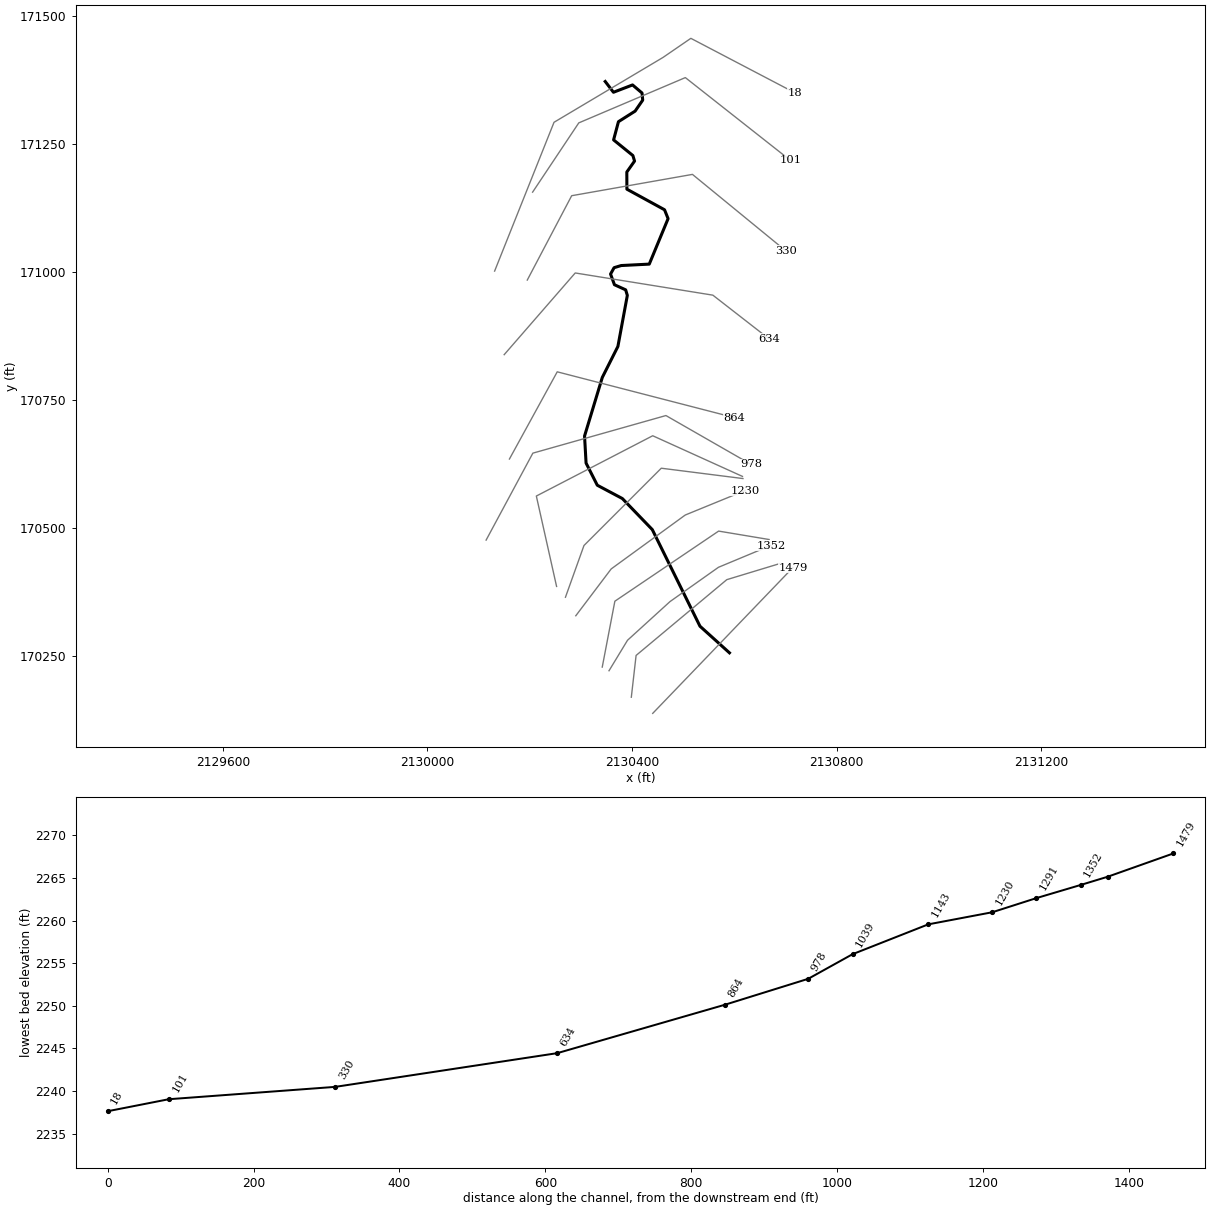
--- CROSRBR.prj (project) ---

Proj Title=CROSRBR
Current Plan=p01
Default Exp/Contr=0,0
English Units
Geom File=g01
Flow File=f01
Plan File=p01
Background Map Layer=Inundation Boundary (01pct Value_0)
BEGIN DESCRIPTION:
Stream Name: Crosier Branch
Flood Zone: A
Monroe County, West Virginia
HEC-RAS Version: 5.0.7
Vertical Datum: NAVD88
Projection: NAD 1983 StatePlane West Virginia S FIPS 4702 (US Feet)
LiDAR: 2016, 1-meter
Land Use: 2016 NLCD
Hydrology Method:
Regression.
Model Notes:
None
END DESCRIPTION:
DSS File=dss
DSS Export Rating Curves= 0
DSS Export Rating Curve Sorted= 0
DSS Export Volume Flow Curves= 0
DXF Filename=SFRKPTTSCKT1.
DXF OffsetX= 0
DXF OffsetY= 0
DXF ScaleX= 0
DXF ScaleY= 0

--- CROSRBR.p01 (plan) ---

Plan Title=Floodplain
Program Version=5.07
Short Identifier=Floodplain
Geom File=g01
Flow File=f01
Subcritical Flow
K Sum by GR= 0
Std Step Tol= 0.01
Critical Tol= 0.01
Num of Std Step Trials= 20
Max Error Tol= 0.3
Flow Tol Ratio= 0.001
Split Flow NTrial= 30
Split Flow Tol= 0.02
Split Flow Ratio= 0.02
Log Output Level= 0
Friction Slope Method= 1
Unsteady Friction Slope Method= 2
Unsteady Bridges Friction Slope Method= 1
Parabolic Critical Depth
Global Vel Dist= 0 , 0 , 0
Global Log Level= 0
CheckData=True
Encroach Param=-1 ,0,0, 0
Computation Interval=0.1SEC
Output Interval=1MIN
Instantaneous Interval=Max Profile
Mapping Interval=1HOUR
Computation Time Step Use Courant=        0
Computation Time Step Use Time Series=    0
Computation Time Step Count To Double=0
Computation Time Step Max Doubling=0
Computation Time Step Max Halving=0
Computation Time Step Residence Courant=0
Run HTab= 0
Run UNet= 0
Run Sediment= 0
Run PostProcess= 0
Run WQNet= 0
Run RASMapper=-1
UNET Theta= 0
UNET Theta Warmup= 0
UNET ZTol= 0
UNET ZSATol= 0
UNET MxIter= 0
UNET Max Iter WO Improvement= 0
UNET MaxInSteps= 0
UNET DtIC= 0
UNET DtMin= 0
UNET MaxCRTS= 0
UNET WFStab= 0
UNET SFStab= 0
UNET WFX= 1
UNET SFX= 1
UNET 1D Methodology=Finite Difference
UNET DSS MLevel= 1
UNET Pardiso=0
UNET DZMax Abort= 0
UNET Use Existing IB Tables= 0
UNET Froude Reduction=False
UNET Froude Limit= 0
UNET Froude Power= 0
UNET D1 Cores= 0
UNET D2 Coriolis=0
UNET D2 Cores= 0
UNET D2 Theta= 1
UNET D2 Theta Warmup= 1
UNET D2 Z Tol= 0.01
UNET D2 Volume Tol= 0.01
UNET D2 Max Iterations= 20
UNET D2 Equation= 0
UNET D2 RampUpFraction=0.1
UNET D2 TimeSlices= 1
UNET D2 BCVolumeCheck=0
UNET D1D2 MaxIter= 0
UNET D1D2 ZTol=0.01
UNET D1D2 QTol=0.1
UNET D1D2 MinQTol=1
DSS File=dss
Write IC File= 0
Write IC File at Fixed DateTime=0
Write IC File at Sim End=0
Echo Input=False
Echo Parameters=False
Echo Output=False
Write Detailed= 0
HDF Write Warmup=0
HDF Write Time Slices=0
HDF Flush=0
HDF Face Node Velocities=0
HDF Compression= 1
HDF Chunk Size= 1
HDF Spatial Parts= 1
HDF Use Max Rows=0
HDF Fixed Rows= 1
Calibration Method= 0
Calibration Iterations= 20
Calibration Max Change=0.05
Calibration Tolerance=0.2
Calibration Maximum=1.5
Calibration Minimum=0.5
Calibration Optimization Method= 1
WQ AD Non Conservative
WQ ULTIMATE=-1
WQ Max Comp Step=1HOUR
WQ Output Interval=15MIN
WQ Output Selected Increments= 0
WQ Output face flow=0
WQ Output face velocity=0
WQ Output face area=0
WQ Output face dispersion=0
WQ Output cell volume=0
WQ Output cell surface area=0
WQ Output cell continuity=0
WQ Output cumulative cell continuity=0
WQ Output face conc=0
WQ Output face dconc_dx=0
WQ Output face courant=0
WQ Output face peclet=0
WQ Output face adv mass=0
WQ Output face disp mass=0
WQ Output cell mass=0
WQ Output cell source sink temp=0
WQ Output nsm pathways=0
WQ Output nsm derived pathways=0
WQ Output MaxMinRange=-1
WQ Daily Max Min Mean=-1
WQ Daily Range=0
WQ Daily Time=0
WQ Create Restart=0
WQ Fixed Restart=0
WQ System Summary=0
WQ Write To DSS=0
WQ Use Fixed Temperature=0
Sorting and Armoring Iterations= 10
XS Update Threshold= 0.02
Bed Roughness Predictor= 0
Hydraulics Update Threshold= 0.02
Energy Slope Method= 1
Volume Change Method= 1
Sediment Retention Method= 0
XS Weighting Method= 0
Number of US Weighted Cross Sections= 1
Number of DS Weighted Cross Sections= 1
Upstream XS Weight=0
Main XS Weight=1
Downstream XS Weight=0
Number of DS XS's Weighted with US Boundary= 1
Upstream Boundary Weight= 1
Weight of XSs Associated with US Boundary= 0
Number of US XS's Weighted with DS Boundary= 1
Downstream Boundary Weight= 0.5
Weight of XSs Associated with DS Boundary= 0.5
Percentile Method= 0
Sediment Output Level= 3
Mass or Volume Output= 0
Output Increment Type= 1
Profile and TS Output Increment= 1
XS Output Flag= 0
XS Output Increment= 10
Write Gradation File= 0
Read Gradation Hotstart= 0
Write HDF5 File= 1
Write Binary Output= 1
Write DSS Sediment File= 0
SV Curve= 0
Specific Gage Flag= 0

--- CROSRBR.f01 (steady flow) ---

Flow Title=Flow
Program Version=5.07
Number of Profiles= 6
Profile Names=01pct,10pct,04pct,02pct,0_2pct,01plus
River Rch & RM=CROSRBR,Main            ,1479
     507     267     356     429     710     750
Boundary for River Rch & Prof#=CROSRBR,Main            , 1
Up Type= 0
Dn Type= 3
Dn Slope=0.0167
Boundary for River Rch & Prof#=CROSRBR,Main            , 2
Up Type= 0
Dn Type= 3
Dn Slope=0.0167
Boundary for River Rch & Prof#=CROSRBR,Main            , 3
Up Type= 0
Dn Type= 3
Dn Slope=0.0167
Boundary for River Rch & Prof#=CROSRBR,Main            , 4
Up Type= 0
Dn Type= 3
Dn Slope=0.0167
Boundary for River Rch & Prof#=CROSRBR,Main            , 5
Up Type= 0
Dn Type= 3
Dn Slope=0.0167
Boundary for River Rch & Prof#=CROSRBR,Main            , 6
Up Type= 0
Dn Type= 3
Dn Slope=0.0167
DSS Import GetInterval= 0
DSS Import GetPeak= 0
DSS Import FillOption= 0

--- CROSRBR.g01 (geometry) ---

Geom Title=Geometry
Program Version=5.07

River Reach=CROSRBR         ,Main
Reach XY= 30
      2130590.51      170255.714     2130532.862      170307.758
     2130439.686        170496.6     2130381.092      170557.364
     2130332.152      170583.372       2130310.2      170626.692
     2130307.226      170679.575     2130341.912      170794.094
     2130372.411      170854.673     2130390.857      170954.499
     2130387.602       170965.35     2130365.684      170975.376
     2130358.045      170996.209     2130364.989      171008.709
     2130378.878      171012.876     2130433.739      171015.654
     2130470.545      171104.543     2130463.601      171121.904
     2130389.989      171162.181     2130389.851      171195.691
     2130404.963      171217.086     2130401.708      171227.937
     2130364.004      171258.517     2130373.496      171294.126
     2130406.048      171314.742     2130420.941      171336.259
     2130419.639      171350.148     2130401.065      171365.957
     2130363.731      171351.635     2130347.646      171372.674

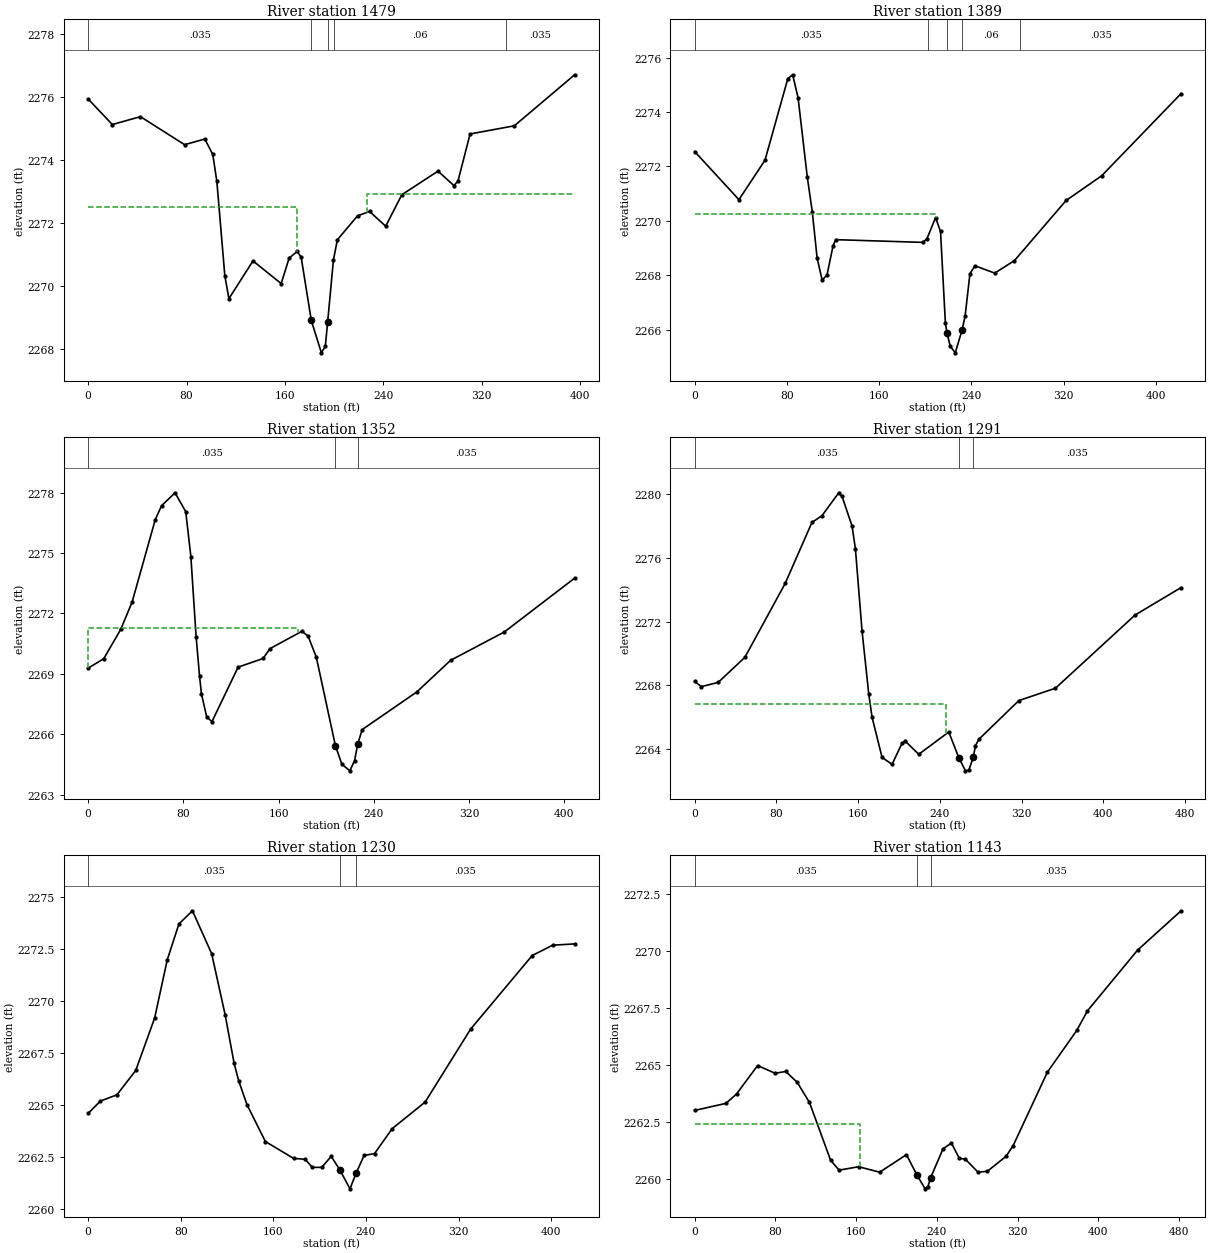
Type RM Length L Ch R = 1 ,1479    ,94.9,90.2,87.1
XS GIS Cut Line= 2
     2130440.498      170137.344     2130714.621      170422.431
#Sta/Elev= 30
       0 2275.95    19.6 2275.14    42.5 2275.39    78.4  2274.5    94.8 2274.68
   101.3 2274.19   104.6 2273.34   111.1 2270.34   114.4 2269.61     134 2270.81
   156.9 2270.09   163.4  2270.9     170 2271.11   173.2 2270.92   181.4 2268.92
   189.6 2267.89   192.8  2268.1  194.732268.878   199.4 2270.84   202.6 2271.48
     219 2272.24   228.8 2272.38   241.9 2271.91     255 2272.91   284.4 2273.66
   297.4  2273.2   300.7 2273.35   310.5 2274.84   346.5  2275.1   395.5 2276.72
#Mann= 5 ,-1 , 0
       0    .035       0   181.4    .045       0  194.73    .035       0
     200     .06       0     340    .035       0
#XS Ineff= 2 , 0
          169.63 2272.52  226.36         2272.94
Permanent Ineff=
       F       F
Bank Sta=181.4,194.73
XS Rating Curve= 0 ,0
Exp/Cntr=0.3,0.1

Type RM Length L Ch R = 1 ,1389    ,37.6,37.2,34.4
XS GIS Cut Line= 4
2130398.65403635170168.9420362782130407.98726622170250.607797706
 2130585.3186339170398.7728220122130689.15081628170430.272472849
#Sta/Elev= 30
       0 2272.55    38.4 2270.78      61 2272.23    80.8 2275.23      85 2275.37
    89.7 2274.52    97.7  2271.6     102 2270.34   106.2 2268.63   110.6 2267.82
   114.8 2268.02     120 2269.08   122.3 2269.31   197.8 2269.21   201.5 2269.35
   208.9 2270.12   213.2 2269.61   217.4 2266.26   218.82265.874   221.7 2265.39
     226 2265.15   231.8 2265.98   234.5 2266.49   238.7 2268.06   243.1 2268.35
   260.2 2268.08   277.3 2268.54   322.1 2270.75     353 2271.66   421.8 2274.68
#Mann= 5 ,-1 , 0
       0    .035       0   202.2     .06       0   218.8    .045       0
   231.8     .06       0   282.2    .035       0
#XS Ineff= 2 , 0
          208.93 2270.25
Permanent Ineff=
       F       F
Bank Sta=218.8,231.8
XS Rating Curve= 0 ,0
Exp/Cntr(USF)=0,0
Exp/Cntr=0.3,0.1

Type RM Length L Ch R = 1 ,1352    ,60.8,60.6,60.1
XS GIS Cut Line= 5
2130355.05205367170220.6966331632130391.24155767170280.302875046
2130474.26453744170355.8750745752130568.99588614170422.932096693
2130671.17801508170465.507983752
#Sta/Elev= 30
       0 2269.28    13.1 2269.75    27.4 2271.21    36.9 2272.56    56.4 2276.66
    61.7 2277.35      73 2277.99      82 2277.05    86.3 2274.82    90.7 2270.85
    93.6 2268.88    95.2    2268    99.6 2266.86     104 2266.62     126 2269.33
     147 2269.76   152.8 2270.25   179.6 2271.11   184.8 2270.87   191.7 2269.83
   207.8 2265.42   213.2 2264.51   219.9 2264.18   223.9 2264.69   226.4 2265.49
   230.3 2266.23   276.2  2268.1   304.6 2269.67   349.8 2271.08   408.8 2273.75
#Mann= 3 ,-1 , 0
       0    .035       0   207.8    .045       0   226.4    .035       0
#XS Ineff= 2 , 0
          176.22 2271.27
Permanent Ineff=
       F       F
Bank Sta=207.8,226.4
XS Rating Curve= 0 ,0
Exp/Cntr(USF)=0,0
Exp/Cntr=0.3,0.1

Type RM Length L Ch R = 1 ,1291    ,59.4,60.5,61.1
XS GIS Cut Line= 4
     2130341.814      170227.804     2130366.485      170356.642
     2130569.336      170493.703      2130668.02      170477.256
#Sta/Elev= 30
       0 2268.25     6.6 2267.93      23 2268.19    49.2 2269.77    88.6 2274.41
   114.8 2278.24   124.6 2278.66     141  2280.1   144.2 2279.88     154 2278.02
   157.3 2276.59   163.8 2271.43   170.4 2267.45   173.6 2266.01   183.4 2263.48
   193.2 2263.05     203 2264.38   206.3 2264.49   219.3 2263.68   248.7 2265.08
   258.5 2263.46     265 2262.64   268.3 2262.68  272.672263.505   274.8 2264.22
   278.1 2264.62   317.2 2267.05   353.1 2267.83   430.9 2272.42     476 2274.15
#Mann= 3 ,-1 , 0
       0    .035       0   258.5    .045       0  272.67    .035       0
#XS Ineff= 2 , 0
           245.7 2266.83
Permanent Ineff=
       F       F
Bank Sta=258.5,272.67
XS Rating Curve= 0 ,0
Exp/Cntr=0.3,0.1

Type RM Length L Ch R = 1 ,1230    ,85.2,87.7,90.4
XS GIS Cut Line= 4
2130290.12382591170328.2007479872130359.30964238170419.738905164
2130504.06765838170525.1142256342130621.15134779170573.012098576
#Sta/Elev= 30
       0  2264.6    10.5 2265.19    24.8 2265.49    41.1 2266.66    57.4 2269.17
    68.3 2271.96    78.4 2273.69    90.1 2274.32   106.7 2272.26   118.3 2269.34
   126.1    2267     130 2266.17   137.2 2265.02   153.1 2263.25   177.5 2262.44
   187.4  2262.4   193.7 2262.01   201.8 2262.01     210 2262.54   217.52261.885
   226.2 2260.98   231.52261.735   238.4 2262.58   247.4 2262.67   262.7 2263.87
   291.1 2265.14   330.4 2268.64   383.6 2272.17   401.3 2272.67   420.3 2272.73
#Mann= 3 ,-1 , 0
       0    .035       0   217.5    .045       0   231.5    .035       0
Bank Sta=217.5,231.5
XS Rating Curve= 0 ,0
Exp/Cntr(USF)=0,0
Exp/Cntr=0.3,0.1

Type RM Length L Ch R = 1 ,1143    ,105.5,103.7,97.6
XS GIS Cut Line= 4
2130269.90027955170364.3902519872130306.08978355170465.507983752
2130457.23418261170616.6523828112130616.89375908170596.428836458
#Sta/Elev= 30
       0    2263      31 2263.31    41.5 2263.72    62.4 2264.97    79.8 2264.63
    90.3 2264.71   101.7 2264.23   113.8 2263.35   134.7 2260.82   143.1 2260.38
   162.5 2260.53   183.4 2260.29   209.9 2261.06   220.5 2260.15   228.4 2259.56
   231.2 2259.66   233.92260.051   246.1 2261.31   254.4 2261.57   262.3  2260.9
   268.3 2260.86   280.9 2260.29   290.1 2260.33   308.7 2260.99   315.7 2261.46
   349.6 2264.68   378.7 2266.51   389.3 2267.37   438.9 2270.03   482.1 2271.76
#Mann= 3 ,-1 , 0
       0    .035       0   220.5    .045       0   233.9    .035       0
#XS Ineff= 2 , 0
          164.04 2262.42
Permanent Ineff=
       F       F
Bank Sta=220.5,233.9
XS Rating Curve= 0 ,0
Exp/Cntr(USF)=0,0
Exp/Cntr=0.3,0.1

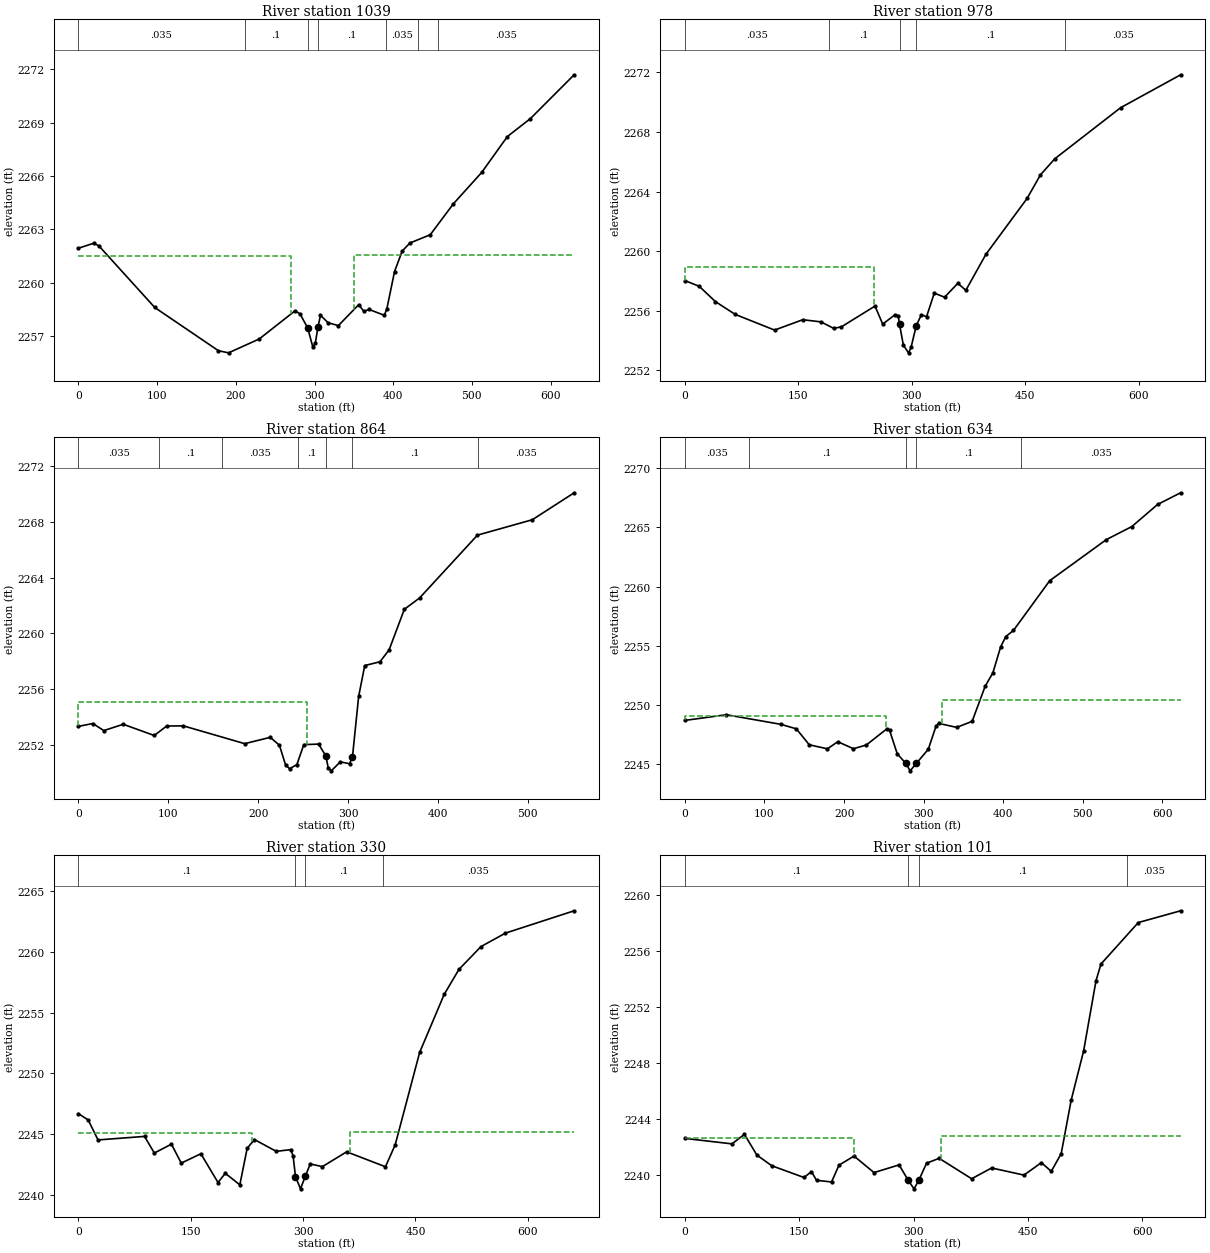
Type RM Length L Ch R = 1 ,1039    ,63.3,60.9,59.8
XS GIS Cut Line= 4
     2130252.542      170385.516     2130212.977      170562.234
     2130440.498      170680.107     2130615.937      170600.611
#Sta/Elev= 30
       0 2261.94    19.4 2262.22    25.9 2262.08      97 2258.61   177.9 2256.18
   190.8 2256.06   229.8 2256.84   275.2 2258.42   281.6 2258.25   291.4 2257.45
   297.9 2256.38   301.1 2256.62   304.4 2257.51   307.6 2258.17   317.3 2257.75
   330.3 2257.59   356.2 2258.77   362.7 2258.39   369.2  2258.5   388.7 2258.17
   391.9 2258.53   401.7 2260.63   411.4 2261.78   421.1 2262.23   447.1  2262.7
   476.5 2264.44   512.4  2266.2   545.1 2268.22   574.4 2269.23   629.9 2271.69
#Mann= 7 ,-1 , 0
       0    .035       0  211.09      .1       0   291.4    .045       0
   304.4      .1       0  391.09    .035       0  431.09      .1       0
  457.33    .035       0
#XS Ineff= 2 , 0
          270.51  2261.5     350         2261.58
Permanent Ineff=
       F       F
Bank Sta=291.4,304.4
XS Rating Curve= 0 ,0
Exp/Cntr=0.3,0.1

Type RM Length L Ch R = 1 ,978     ,124.3,114.2,101.8
XS GIS Cut Line= 4
2130114.77914501170476.1004919422130206.15617012170646.103413767
2130466.31995296170719.6025990522130633.15143702170623.936992807
#Sta/Elev= 30
       02258.019  19.0252257.634   40.442256.606  66.5132255.749 118.6592254.694
 155.9072255.391 180.1442255.245 196.9052254.807 207.1332254.916 251.4532256.306
 261.6812255.096 277.9632255.728 282.136 2255.66 283.8752255.092 288.9552253.687
 295.7732253.166 299.1822253.534 306.0012254.987 312.819 2255.73 319.638 2255.59
 329.8662257.176 343.5032256.904 360.9652257.835 371.5982257.369  398.182259.786
 452.5992263.538 470.3332265.126 489.2432266.201 576.2282269.629 655.6652271.844
#Mann= 5 ,-1 , 0
       0    .035       0     190      .1       0 283.875    .045       0
 306.001      .1       0  503.35    .035       0
#XS Ineff= 2 , 0
          250.72 2258.92
Permanent Ineff=
       F       F
Bank Sta=283.875,306.001
XS Rating Curve= 0 ,0
Exp/Cntr(USF)=0,0
Exp/Cntr=0.3,0.1

Type RM Length L Ch R = 1 ,864     ,219.8,229.8,213.1
XS GIS Cut Line= 3
2130160.36123278170634.5989971022130253.80988071170805.093770122
      2130599.49      170715.743
#Sta/Elev= 30
       02253.313  16.069 2253.52  28.2352253.012  49.9032253.464  84.354 2252.66
  98.237 2253.34  116.742253.351     1852252.073 213.4672252.528 223.6332251.958
  230.412250.553 234.9212250.276 242.9992250.565 250.7422252.004 267.2332252.042
 275.3112251.179 277.8512250.356  281.242250.122 291.4062250.769 301.5722250.632
 304.8152251.094 311.738 2255.46 318.515 2257.68 335.4582257.952 345.6242258.806
 362.568 2261.72 379.5112262.531 443.8962267.044 504.8912268.148 551.4662270.085
#Mann= 7 ,-1 , 0
       0    .035       0      90      .1       0     160    .035       0
  244.43      .1       0 275.311    .045       0 304.815      .1       0
  444.43    .035       0
#XS Ineff= 2 , 0
          254.44 2255.05
Permanent Ineff=
       F       F
Bank Sta=275.311,304.815
XS Rating Curve= 0 ,0
Exp/Cntr=0.3,0.1

Type RM Length L Ch R = 1 ,634     ,259.4,304.5,265.3
XS GIS Cut Line= 4
     2130150.111      170838.641        2130289.      170998.363
     2130558.097      170954.961     2130667.472      170869.891
#Sta/Elev= 30
       0  2248.7    52.1 2249.18   120.5 2248.37     140 2247.99   156.3 2246.64
   179.1  2246.3   192.1  2246.9   211.7 2246.31   227.9 2246.62   253.8 2247.99
   257.1 2247.88   266.8 2245.88   277.42245.085     283 2244.44   290.8 2245.07
   305.8 2246.26   315.5 2248.21   318.8 2248.45   341.5 2248.11   360.9 2248.62
   377.2 2251.58   386.9 2252.71   396.6 2254.89   403.1 2255.78   412.8  2256.3
   458.3  2260.5   529.4 2263.97   561.6 2265.08   593.8 2266.94   622.8 2267.93
#Mann= 5 ,-1 , 0
       0    .035       0      80      .1       0   277.4    .045       0
   290.8      .1       0  421.66    .035       0
#XS Ineff= 2 , 0
          252.71 2249.08  322.71         2250.41
Permanent Ineff=
       F       F
Bank Sta=277.4,290.8
XS Rating Curve= 0 ,0
Exp/Cntr=0.3,0.1

Type RM Length L Ch R = 1 ,330     ,152.1,228.2,189.7
XS GIS Cut Line= 4
      2130195.25      170984.475     2130282.055      171149.405
     2130518.167      171191.072     2130700.458      171041.766
#Sta/Elev= 30
       0 2246.68    13.1 2246.15    26.2 2244.51    88.3  2244.8   101.4 2243.43
   124.2 2244.16   137.3  2242.6   163.5 2243.37   186.4    2241   196.1 2241.76
   215.5 2240.81   225.3 2243.82     235 2244.54   264.1 2243.57   283.6 2243.71
   286.7 2243.16  289.782241.484   296.5 2240.48     303 2241.53   309.5 2242.53
   325.7 2242.31   358.1 2243.53   409.9  2242.3   422.9 2244.11   455.6 2251.73
   488.3  2256.5     508 2258.56   537.4 2260.44   570.1 2261.55   661.8 2263.39
#Mann= 4 ,-1 , 0
       0      .1       0  289.78    .045       0     303      .1       0
  406.38    .035       0
#XS Ineff= 2 , 0
          231.96 2245.09  363.04         2245.16
Permanent Ineff=
       F       F
Bank Sta=289.78,303
XS Rating Curve= 0 ,0
Exp/Cntr=0.3,0.1

Type RM Length L Ch R = 1 ,101     ,33.8,83.8,47.4
XS GIS Cut Line= 4
     2130205.667       171156.35     2130295.944      171291.766
     2130504.278      171380.308     2130709.139       171218.85
#Sta/Elev= 30
       0 2242.63    61.8 2242.24    78.1 2242.92    94.4 2241.44   113.9 2240.68
   156.2 2239.84     166 2240.26   172.6 2239.64   192.3 2239.52   202.1 2240.72
   221.8 2241.37     248 2240.19   280.9 2240.74  292.532239.667   300.5 2239.03
   306.9 2239.66   316.9 2240.86   333.4 2241.21     376 2239.75   402.2 2240.52
   444.6 2240.01   467.4  2240.9   480.4 2240.28   493.4 2241.54   506.5 2245.36
   522.8 2248.87   539.1  2253.9   545.6 2255.08   594.5 2258.04     650 2258.88
#Mann= 4 ,-1 , 0
       0      .1       0  292.53    .045       0   306.9      .1       0
  579.12    .035       0
#XS Ineff= 2 , 0
          221.63 2242.66  335.96         2242.77
Permanent Ineff=
       F       F
Bank Sta=292.53,306.9
XS Rating Curve= 0 ,0
Exp/Cntr=0.3,0.1

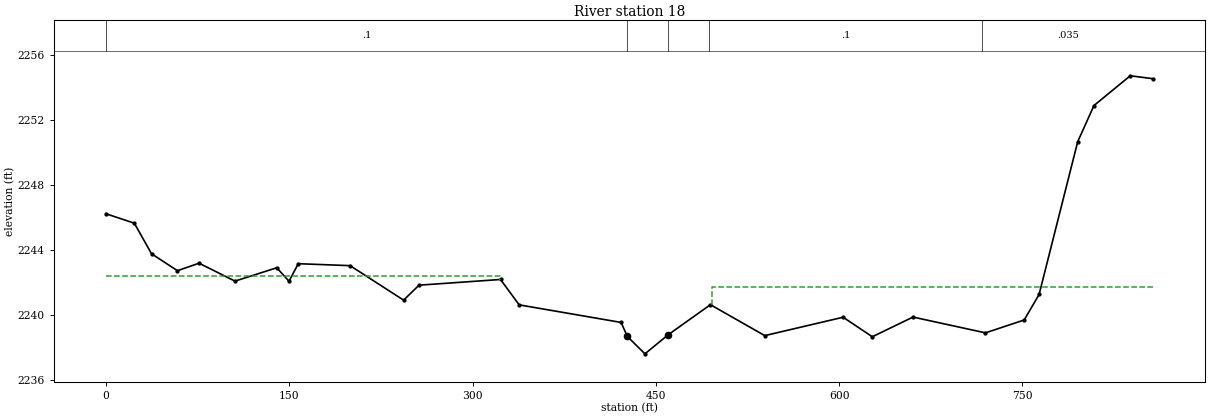
Type RM Length L Ch R = 1 ,18      ,,,
XS GIS Cut Line= 5
2130131.39009695171002.010066359   2130247.55207171292.947852078
2130460.69330496171419.7668868792130515.04431988171457.066602996
2130718.59419926171350.495985517
#Sta/Elev= 30
       0 2246.23    23.2 2245.65    37.3 2243.77    58.5 2242.73    76.2 2243.19
   105.6 2242.09   139.8 2242.91   149.8 2242.08   157.4 2243.16   199.8 2243.04
   243.6 2240.92   256.2 2241.84   322.9 2242.19   338.2 2240.63   421.6 2239.55
   426.7 2238.69   441.1 2237.62   460.1 2238.79   494.7 2240.64   539.2 2238.74
   603.3 2239.87   627.2 2238.67   660.5 2239.88   719.8 2238.91   751.5  2239.7
   763.7 2241.27   795.3 2250.66   808.6 2252.88   838.3 2254.71856.9664 2254.53
#Mann= 5 ,-1 , 0
       0      .1       0   426.7    .045       0   460.1    .035       0
  493.27      .1       0  717.21    .035       0
#XS Ineff= 2 , 0
          322.35 2242.43   495.7          2241.7
Permanent Ineff=
       F       F
Bank Sta=426.7,460.1
XS Rating Curve= 0 ,0
Exp/Cntr(USF)=0,0
Exp/Cntr=0.3,0.1
LCMann Table=0

Chan Stop Cuts=-1
Use User Specified Reach Order=0
Composite Channel Slope=5